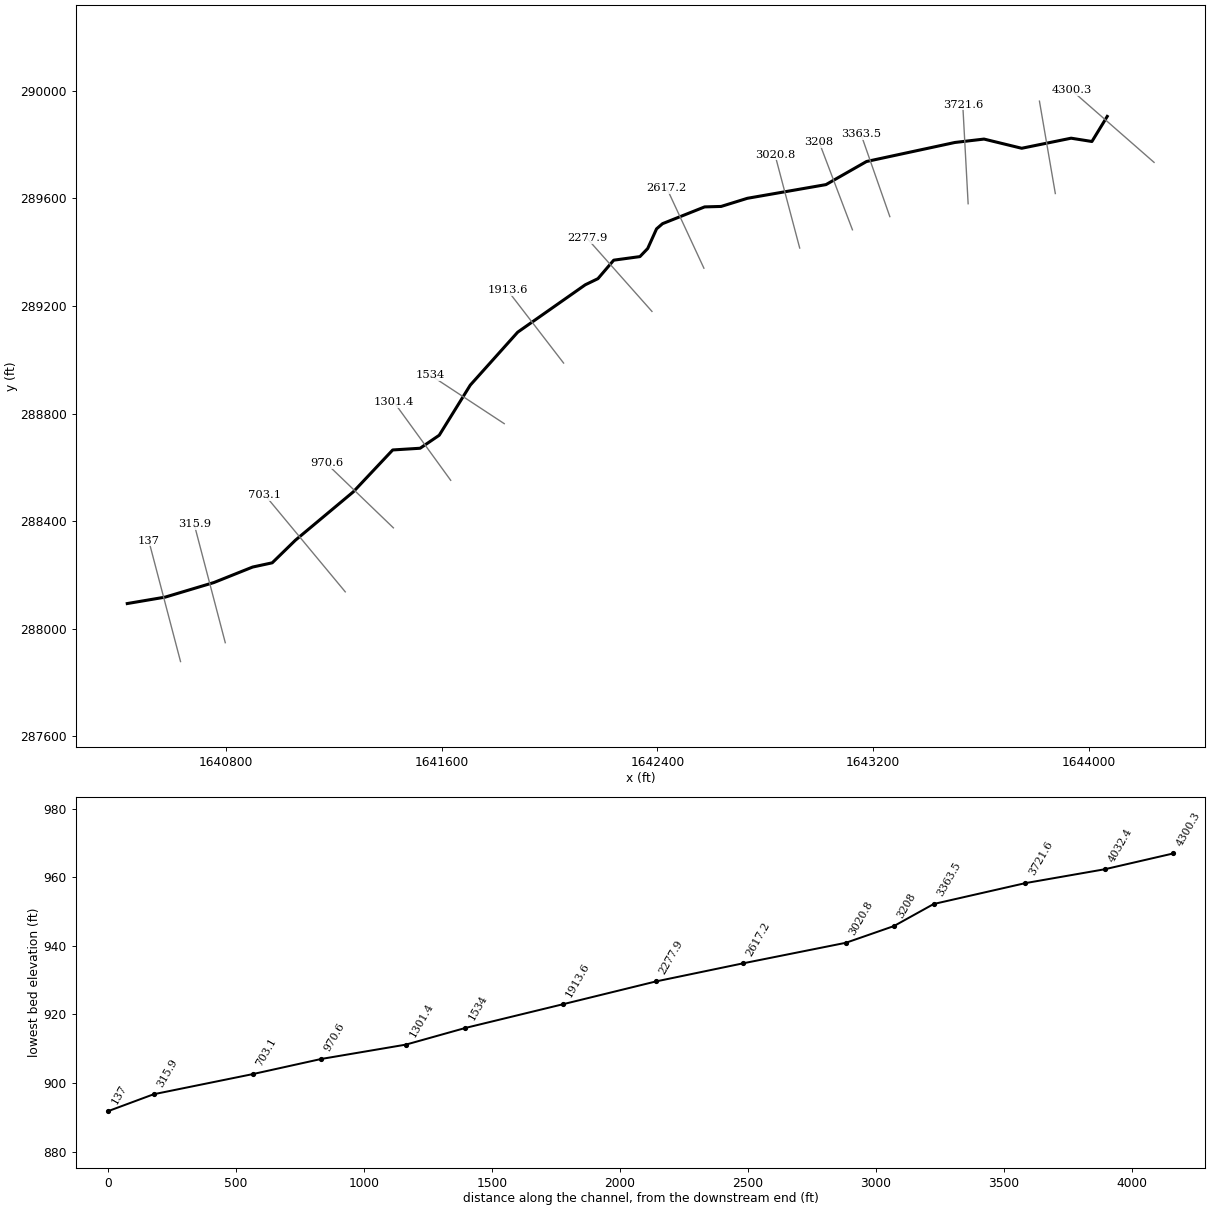
--- np11.prj (project) ---

Proj Title=np11
Current Plan=p01
Default Exp/Contr=0,0
English Units
Geom File=g01
Flow File=f01
Plan File=p01
BEGIN DESCRIPTION:
END DESCRIPTION:
DSS Export Rating Curves= 0
DSS Export Rating Curve Sorted= 0
DSS Export Volume Flow Curves= 0
DXF OffsetX= 0
DXF OffsetY= 0
DXF ScaleX= 0
DXF ScaleY= 0

--- np11.p01 (plan) ---

Plan Title=Approximate Study - 100yr
Program Version=4.00
Geom File=g01
Flow File=f01
Subcritical Flow
K Sum by GR= 0
Std Step Tol= 0.01
Critical Tol= 0.01
Num of Std Step Trials= 20
Max Error Tol= 0.3
Flow Tol Ratio= 0.001
Split Flow NTrial= 30
Split Flow Tol= 0.02
Split Flow Ratio= 0.02
Log Output Level= 0
Friction Slope Method= 1
Unsteady Friction Slope Method= 2
Unsteady Bridges Friction Slope Method= 1
Parabolic Critical Depth
Global Vel Dist= 0 , 0 , 0
Global Log Level= 0
CheckData=True
Encroach Param=-1 ,0,0, 0
Run HTab= 0
Run UNet= 0
Run PostProcess= 0
Run WQNet= 0
UNET Theta= 0
UNET Theta Warmup= 0
UNET ZTol= 0
UNET ZSATol= 0
UNET MxIter= 0
UNET MaxInSteps= 0
UNET DtIC= 0
UNET DtMin= 0
UNET MaxCRTS= 0
UNET WFStab= 0
UNET SFStab= 0
UNET WFX= 1
UNET SFX= 1
UNET DSS MLevel= 1
UNET DZMax Abort= 0
UNET Convert EG Bridges= 0
UNET Use Existing IB Tables= 0
UNET Froude Reduction=False
UNET Froude Limit= 0
UNET Froude Power= 0
UNET Time Slicing=0,0, 5
Write IC File= 0
Echo Input=False
Echo Output=False
Write Detailed= 0
Detailed Automatic Start=False, 0
WQ ULTIMATE=-1
WQ Max Comp Step=1HOUR
WQ Output Interval=15MIN
WQ Output Selected Increments= 0
WQ Output face flow=0
WQ Output face velocity=0
WQ Output face area=0
WQ Output face dispersion=0
WQ Output cell volume=0
WQ Output cell surface area=0
WQ Output cell continuity=0
WQ Output face conc=0
WQ Output face dconc_dx=0
WQ Output face courant=0
WQ Output face peclet=0
WQ Output face adv mass=0
WQ Output face disp mass=0
WQ Output cell mass=0
WQ Output cell source sink temp=0
WQ Output cell source sink nsm=0
WQ Output MaxMinRange=-1
WQ Daily Max Min Mean=-1
WQ Daily Range=0
WQ Daily Time=0
WQ Create Restart=0
WQ Fixed Restart=0
WQ System Summary=False
Sorting and Armoring Iterations= 10
XS Update Threshold= 0.02
Hydraulics Update Threshold= 0.02
Energy Slope Method= 1
Volume Change Method= 0
XS Weighting Method= 0
Number of US Weighted Cross Sections= 1
Number of DS Weighted Cross Sections= 1
Upstream XS Weight=0.25
Main XS Weight=0.5
Downstream XS Weight=0.25
Number of DS XS's Weighted with US Boundary= 1
Upstream Boundary Weight= 1
Weight of XSs Associated with US Boundary= 0
Number of US XS's Weighted with DS Boundary= 1
Downstream Boundary Weight= 0.5
Weight of XSs Associated with DS Boundary= 0.5
Sediment Output Level= 4
Mass or Volume Output= 0
Output Increment Type= 1
Profile and TS Output Increment= 10
XS Output Flag= 0
XS Output Increment= 10
Disregard all LS=0
Disregard all Conn=0
Disregard all Breaches=0
Disregard all Pumps=0

--- np11.f01 (steady flow) ---

Flow Title=USGS Regression Equation
Program Version=4.00
Number of Profiles= 1
Profile Names=P100yr
River Rch & RM=np11,Main            ,4300.3
     309
River Rch & RM=np11,Main            ,4032.4
     309
River Rch & RM=np11,Main            ,3721.6
     510
River Rch & RM=np11,Main            ,1913.6
     547
River Rch & RM=np11,Main            ,137
     602
Boundary for River Rch & Prof#=np11,Main            , 1
Up Type= 0
Dn Type= 3
Dn Slope=0.019764
DSS Import GetInterval= 0
DSS Import GetPeak= 0
DSS Import FillOption= 0

--- np11.g01 (geometry) ---

Geom Title=USGS 3m DEM
Program Version=4.00

River Reach=np11            ,Main
Reach XY= 30
     1644068.453      289904.715     1644011.629      289811.452
     1643934.508      289823.741     1643751.172      289786.284
     1643611.386      289820.456      1643503.49      289807.846
      1643175.43      289737.048     1643025.174      289651.211
     1642733.589      289600.302     1642636.184      289570.049
     1642575.073       289568.35     1642418.949       289506.03
     1642396.719      289486.766     1642363.855      289413.666
     1642335.099      289383.615     1642237.851      289370.332
     1642179.314      289301.635     1642132.286      289278.827
     1641881.607      289102.651     1641705.767      288905.906
     1641590.561      288719.534     1641519.728      288671.226
     1641418.024      288664.869     1641271.823      288509.134
     1641057.185      288329.456     1640971.079      288245.337
     1640898.483      288229.644     1640754.758      288172.038
     1640574.094      288117.854     1640433.358      288093.899

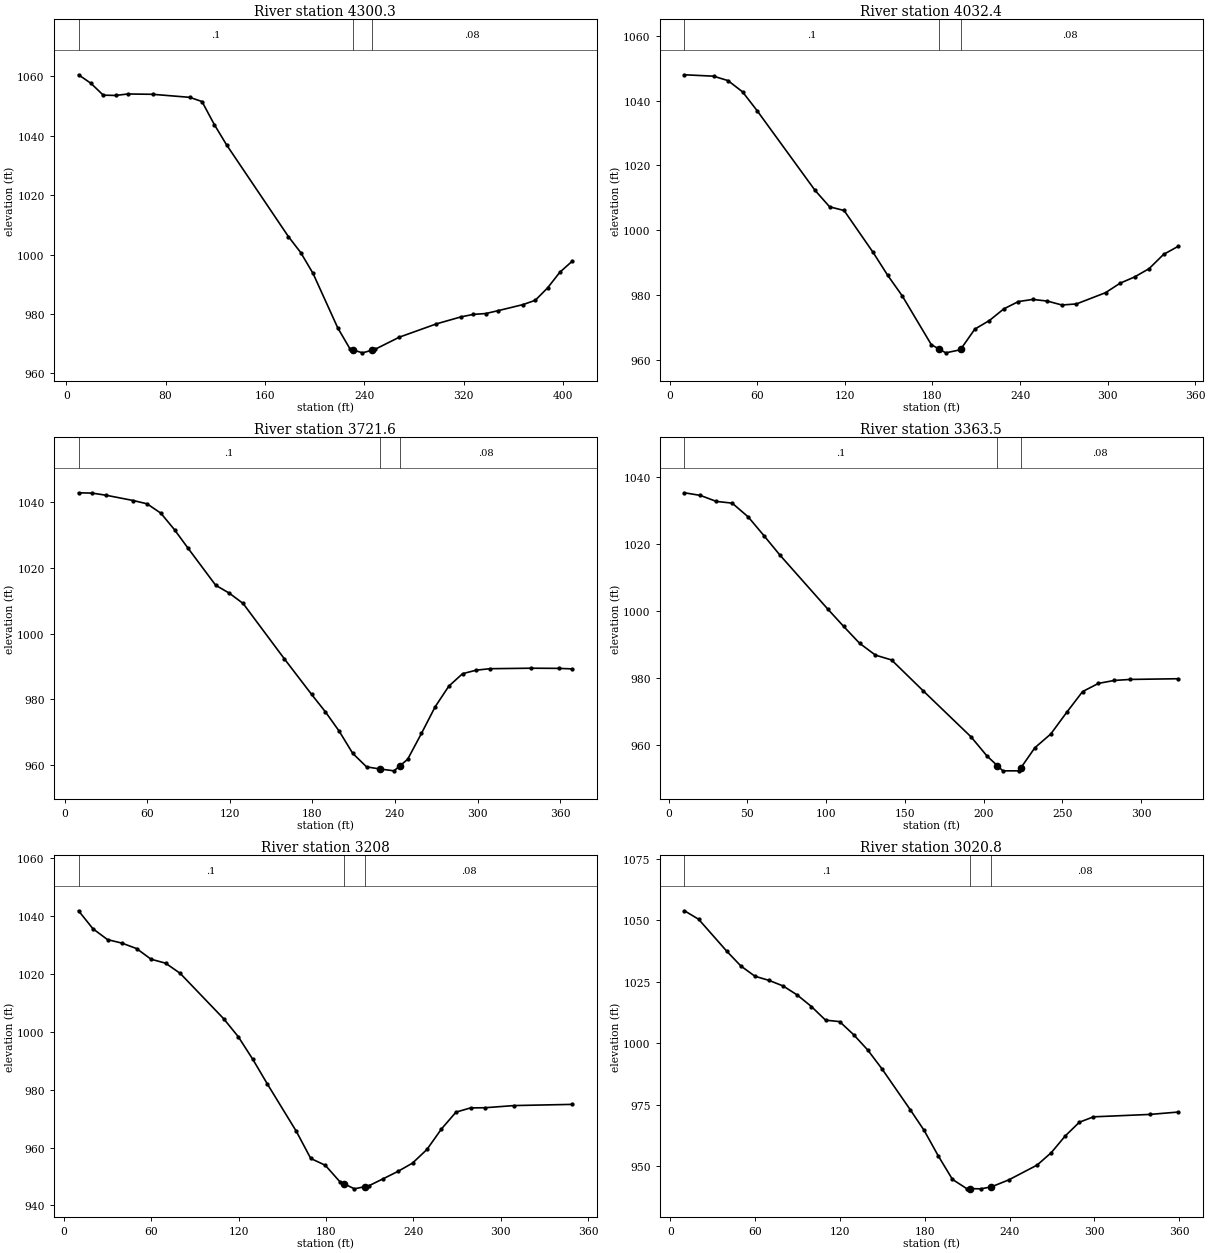
Type RM Length L Ch R = 1 ,4300.3  ,284.1,267.9,251.4
XS GIS Cut Line= 2
     1644242.193      289733.814     1643935.769      290002.309
#Sta/Elev= 30
     9.9 1060.48    19.9  1057.6    29.8 1053.62    39.7 1053.53    49.7 1054.02
    69.6 1053.91    99.4 1052.89   109.3 1051.48   119.2 1043.74   129.2 1036.83
   178.9 1006.02   188.8 1000.66   198.7  993.65   218.6  975.33   228.5  968.23
     231   967.9   238.5  966.92     246  967.78   248.4  968.06   268.3  972.21
   298.1  976.67     318  979.04   327.9  979.86   337.9  980.15   347.8  981.12
   367.7  983.14   377.6  984.59   387.5  988.73   397.5  994.07   407.4  997.75
#Mann= 3 , 0 , 0
     9.9      .1       0     231    .045       0     246     .08       0
Bank Sta=231,246
XS Rating Curve= 0 ,0
Exp/Cntr=0.3,0.1

Type RM Length L Ch R = 1 ,4032.4  ,313.8,310.8,307.9
XS GIS Cut Line= 2
     1643875.882      289618.032     1643816.993      289961.386
#Sta/Elev= 30
      10 1047.93    29.9  1047.5    39.8 1046.14    49.8 1042.68    59.7 1036.93
    99.5 1012.34   109.5 1007.27   119.4 1006.14   139.3  993.23   149.3  986.18
   159.3  979.83   179.2  964.83   184.6 963.456   189.1  962.31   199.1  963.25
   199.6 963.571     209  969.61     219  972.26   228.9  975.85   238.9   978.1
   248.8  978.76   258.8  978.24   268.7  977.04   278.7  977.37   298.6  980.83
   308.6  983.75   318.5  985.67   328.5  988.24   338.4  992.62   348.4   995.1
#Mann= 3 , 0 , 0
      10      .1       0   184.6    .045       0   199.6     .08       0
Bank Sta=184.6,199.6
XS Rating Curve= 0 ,0
Exp/Cntr=0.3,0.1

Type RM Length L Ch R = 1 ,3721.6  ,351.7,358,364.4
XS GIS Cut Line= 2
      1643552.49      289580.103     1643532.528       289948.41
#Sta/Elev= 30
      10  1042.9    19.9  1042.8    29.9 1042.16    49.8 1040.54    59.8 1039.54
    69.8  1036.7    79.8 1031.63    89.7 1025.96   109.7 1014.74   119.6 1012.34
   129.6 1009.21   159.5   992.4   179.4  981.52   189.4  976.23   199.4  970.36
   209.3  963.57   219.3  959.48   228.8 958.834   239.3  958.26   243.8 959.862
   249.2  961.78   259.2  969.63   269.2  977.76   279.1  984.03   289.1  987.83
   299.1  988.91     309  989.35   338.9   989.5   358.9  989.45   368.8  989.29
#Mann= 3 , 0 , 0
      10      .1       0   228.8    .045       0   243.8     .08       0
Bank Sta=228.8,243.8
XS Rating Curve= 0 ,0
Exp/Cntr=0.3,0.1

Type RM Length L Ch R = 1 ,3363.5  ,154.8,155.5,156.1
XS GIS Cut Line= 2
     1643262.037      289532.193     1643155.238      289837.619
#Sta/Elev= 27
    10.1 1035.41    20.2 1034.62    30.3 1032.83    40.4 1032.31    50.6 1028.17
    60.7  1022.5    70.8 1016.71   101.1  1000.6   111.2   995.4   121.3  990.36
   131.4  986.81   141.6  985.37   161.8  976.08   192.1  962.34   202.2  956.63
   208.8 953.725   212.3  952.18   222.4  952.18   223.8 953.128   232.6  959.09
   242.7   963.2   252.8  969.67   262.9   975.9     273  978.36   283.1  979.24
   293.2  979.54   323.6  979.75
#Mann= 3 , 0 , 0
    10.1      .1       0   208.8    .045       0   223.8     .08       0
Bank Sta=208.8,223.8
XS Rating Curve= 0 ,0
Exp/Cntr=0.3,0.1

Type RM Length L Ch R = 1 ,3208    ,189.5,187.2,184.8
XS GIS Cut Line= 2
     1643123.298      289483.285     1642999.531      289809.671
#Sta/Elev= 30
      10 1041.85    19.9 1035.63    29.9 1031.89    39.9 1030.66    49.9 1028.78
    59.8 1025.11    69.8 1023.74    79.8 1020.23   109.7 1004.54   119.7  998.34
   129.7  990.51   139.6  982.07   159.6  965.62   169.5  956.25   179.5  953.89
   189.5  948.21     192  947.59   199.5  945.75     207  946.54   209.4   946.8
   219.4  949.27   229.4  951.78   239.4  954.64   249.3  959.35   259.3  966.46
   269.3  972.27   279.3  973.72   289.2  973.78   309.2  974.53   349.1  974.94
#Mann= 3 , 0 , 0
      10      .1       0     192    .045       0     207     .08       0
Bank Sta=192,207
XS Rating Curve= 0 ,0
Exp/Cntr=0.3,0.1

Type RM Length L Ch R = 1 ,3020.8  ,399.7,403.6,407.5
XS GIS Cut Line= 2
     1642927.666      289415.413     1642835.838       289762.76
#Sta/Elev= 30
      10 1053.84      20  1050.4    39.9 1037.43    49.9 1031.41    59.9 1027.24
    69.9 1025.55    79.8 1023.29    89.8 1019.63    99.8 1014.95   109.8 1009.42
   119.8 1008.81   129.7 1003.51   139.7  997.26   149.7  989.66   169.7  973.07
   179.6  964.59   189.6  954.24   199.6  944.73   209.6  941.02   212.1  940.98
   219.6  940.89   227.1  941.68   239.5  944.54   259.5  950.54   269.5  955.57
   279.4  962.37   289.4  967.95   299.4  970.14   339.3  971.12   359.3  972.08
#Mann= 3 , 0 , 0
      10      .1       0   212.1    .045       0   227.1     .08       0
Bank Sta=212.1,227.1
XS Rating Curve= 0 ,0
Exp/Cntr=0.3,0.1

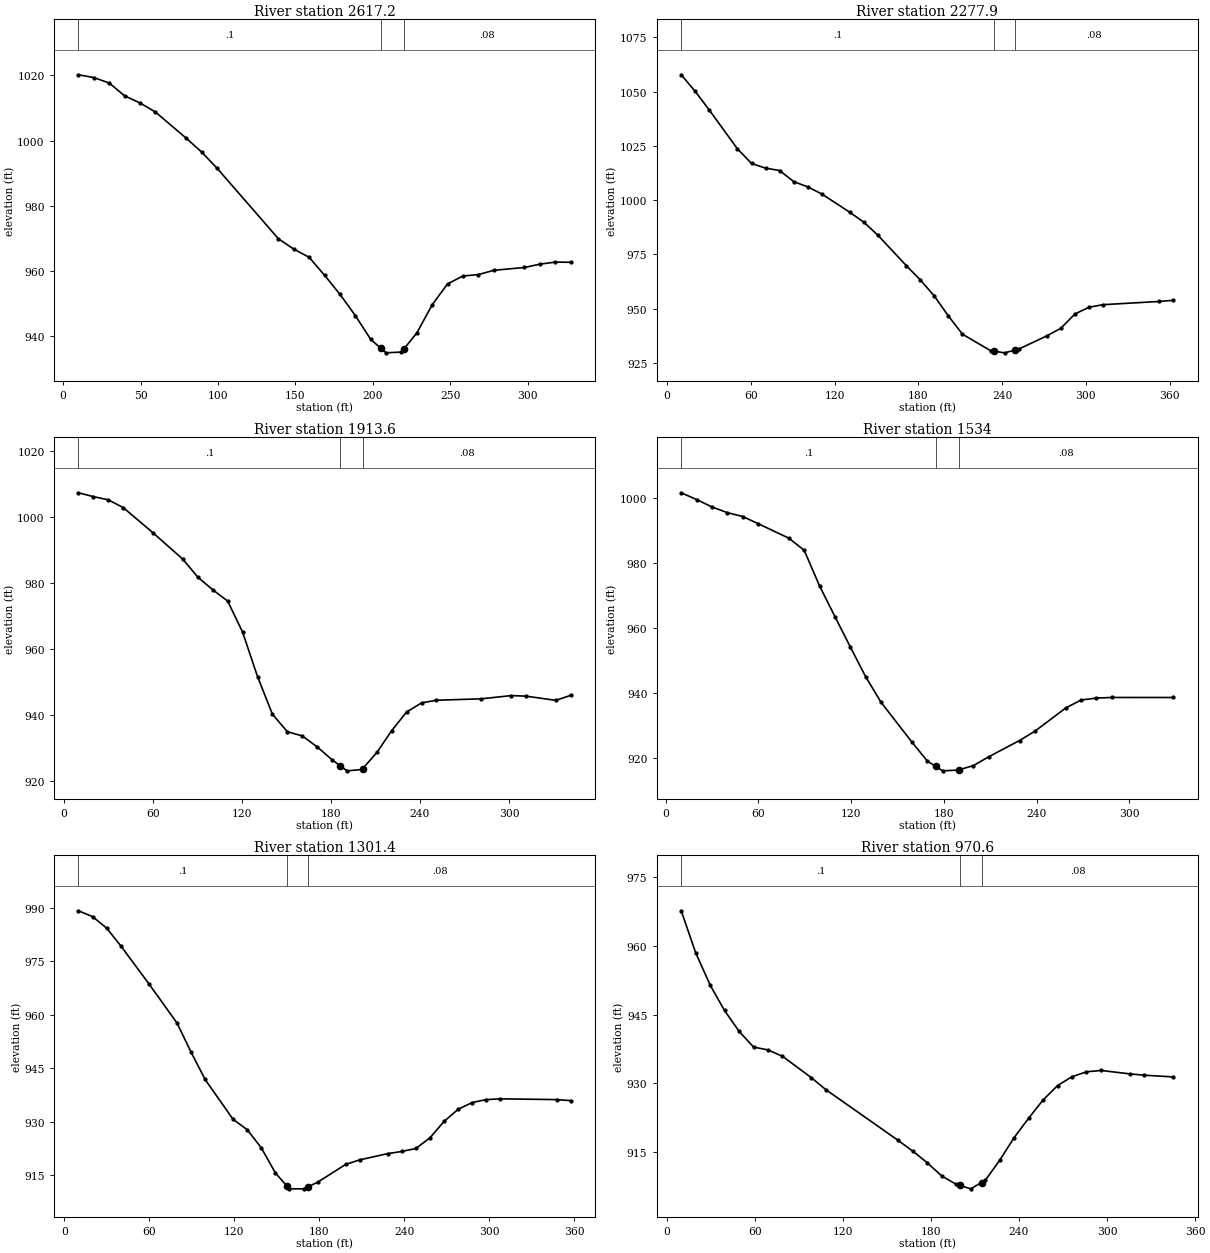
Type RM Length L Ch R = 1 ,2617.2  ,332.7,339.3,346
XS GIS Cut Line= 2
     1642572.334      289340.554     1642434.593      289637.994
#Sta/Elev= 30
     9.9 1020.17    19.9 1019.31    29.8 1017.63    39.7 1013.72    49.7 1011.51
    59.6 1008.75    79.5 1000.72    89.4  996.49    99.3  991.57   139.1  969.84
     149  966.69   158.9  964.18   168.9  958.64   178.8  952.83   188.7  946.32
   198.7  938.98   205.1 936.326   208.6  934.87   218.5  935.12   220.1 936.061
   228.5     941   238.4  949.63   248.3  956.02   258.3  958.45   268.2  958.87
   278.1  960.18     298  961.06   307.9  962.07   317.9  962.71   327.8  962.65
#Mann= 3 , 0 , 0
     9.9      .1       0   205.1    .045       0   220.1     .08       0
Bank Sta=205.1,220.1
XS Rating Curve= 0 ,0
Exp/Cntr=0.3,0.1

Type RM Length L Ch R = 1 ,2277.9  ,365.9,364.3,362.6
XS GIS Cut Line= 2
     1642379.697      289179.856     1642139.149      289451.345
#Sta/Elev= 30
    10.1 1057.73    20.2 1050.03    30.2  1041.5    50.4 1023.58    60.5 1016.86
    70.5 1014.71    80.6 1013.62    90.7 1008.51   100.8 1006.08   110.8  1002.8
     131  994.33   141.1  989.73   151.1  983.73   171.3  969.83   181.4  963.21
   191.4  955.81   201.5  946.61   211.6   938.2   231.7  930.63   234.3  930.37
   241.8  929.61   249.3  930.89   251.9  931.33     272  937.42   282.1  940.94
   292.2  947.54   302.3  950.62   312.3   951.8   352.6  953.28   362.7  953.82
#Mann= 3 , 0 , 0
    10.1      .1       0   234.3    .045       0   249.3     .08       0
Bank Sta=234.3,249.3
XS Rating Curve= 0 ,0
Exp/Cntr=0.3,0.1

Type RM Length L Ch R = 1 ,1913.6  ,372.1,379.6,387.2
XS GIS Cut Line= 2
     1642051.859      288987.919     1641843.705      289258.708
#Sta/Elev= 30
      10 1007.25    20.1 1006.08    30.1 1005.11    40.2 1002.74    60.3  995.09
    80.4  987.07    90.4  981.66   100.5  977.83   110.5  974.42   120.5  965.06
   130.6  951.55   140.6  940.15   150.7   934.8   160.7  933.55   170.8  930.22
   180.8   926.3   186.4 924.444   190.9  922.95   200.9  923.34   201.4 923.596
     211  928.51     221  935.16     231  940.78   241.1  943.55   251.1  944.36
   281.3  944.78   301.4  945.76   311.4   945.6   331.5  944.32   341.5  945.83
#Mann= 3 , 0 , 0
      10      .1       0   186.4    .045       0   201.4     .08       0
Bank Sta=186.4,201.4
XS Rating Curve= 0 ,0
Exp/Cntr=0.3,0.1

Type RM Length L Ch R = 1 ,1534    ,240.8,232.6,224.4
XS GIS Cut Line= 2
     1641831.728      288762.641     1641557.244      288943.301
#Sta/Elev= 28
      10 1001.49    19.9  999.42    29.9  997.15    39.8  995.39    49.8   994.2
    59.7  992.02    79.7  987.54    89.6  983.83    99.6  972.83   109.5  963.47
   119.5  954.11   129.4  944.97   139.4   937.1   159.3  924.93   169.3  919.09
   174.7 917.438   179.2  916.07   189.2   916.3   189.7  916.37   199.2  917.69
   209.1   920.4     229  925.39     239  928.25   258.9  935.38   268.9  937.83
   278.8  938.42   288.8  938.61   328.6   938.6
#Mann= 3 , 0 , 0
      10      .1       0   174.7    .045       0   189.7     .08       0
Bank Sta=174.7,189.7
XS Rating Curve= 0 ,0
Exp/Cntr=0.3,0.1

Type RM Length L Ch R = 1 ,1301.4  ,325.9,330.8,335.7
XS GIS Cut Line= 2
     1641633.101      288552.037     1641423.496      288841.493
#Sta/Elev= 30
     9.9   989.1    19.9  987.45    29.8  984.24    39.7  979.33    59.6  968.66
    79.4   957.7    89.3  949.59    99.3  941.85   119.1  930.67   129.1  927.76
     139  922.69   148.9   915.7   157.3 911.899   158.8  911.22   168.8  911.21
   172.3 911.859   178.7  913.04   198.5  918.04   208.5  919.33   228.3  921.08
   238.3  921.69   248.2  922.53   258.1  925.51     268  930.08     278   933.5
   287.9  935.39   297.8  936.21   307.7  936.42   347.5  936.21   357.4  935.92
#Mann= 3 , 0 , 0
     9.9      .1       0   157.3    .045       0   172.3     .08       0
Bank Sta=157.3,172.3
XS Rating Curve= 0 ,0
Exp/Cntr=0.3,0.1

Type RM Length L Ch R = 1 ,970.6   ,270.1,267.5,265
XS GIS Cut Line= 2
     1641420.501       288375.37     1641171.969      288614.919
#Sta/Elev= 30
     9.9  967.65    19.7  958.54    29.6  951.45    39.4  945.91    49.3  941.38
    59.2  937.93      69  937.32    78.9  935.93    98.6  931.25   108.5  928.64
   157.8  917.57   167.7  915.24   177.5  912.73   187.4  909.83   197.2  908.03
   199.6  907.78   207.1  907.03   214.6  908.41     217  908.86   226.8  913.23
   236.7  918.19   246.6  922.44   256.4  926.39   266.3  929.55   276.1  931.47
     286  932.54   295.9  932.84   315.6  932.09   325.5   931.8   345.2  931.43
#Mann= 3 , 0 , 0
     9.9      .1       0   199.6    .045       0   214.6     .08       0
Bank Sta=199.6,214.6
XS Rating Curve= 0 ,0
Exp/Cntr=0.3,0.1

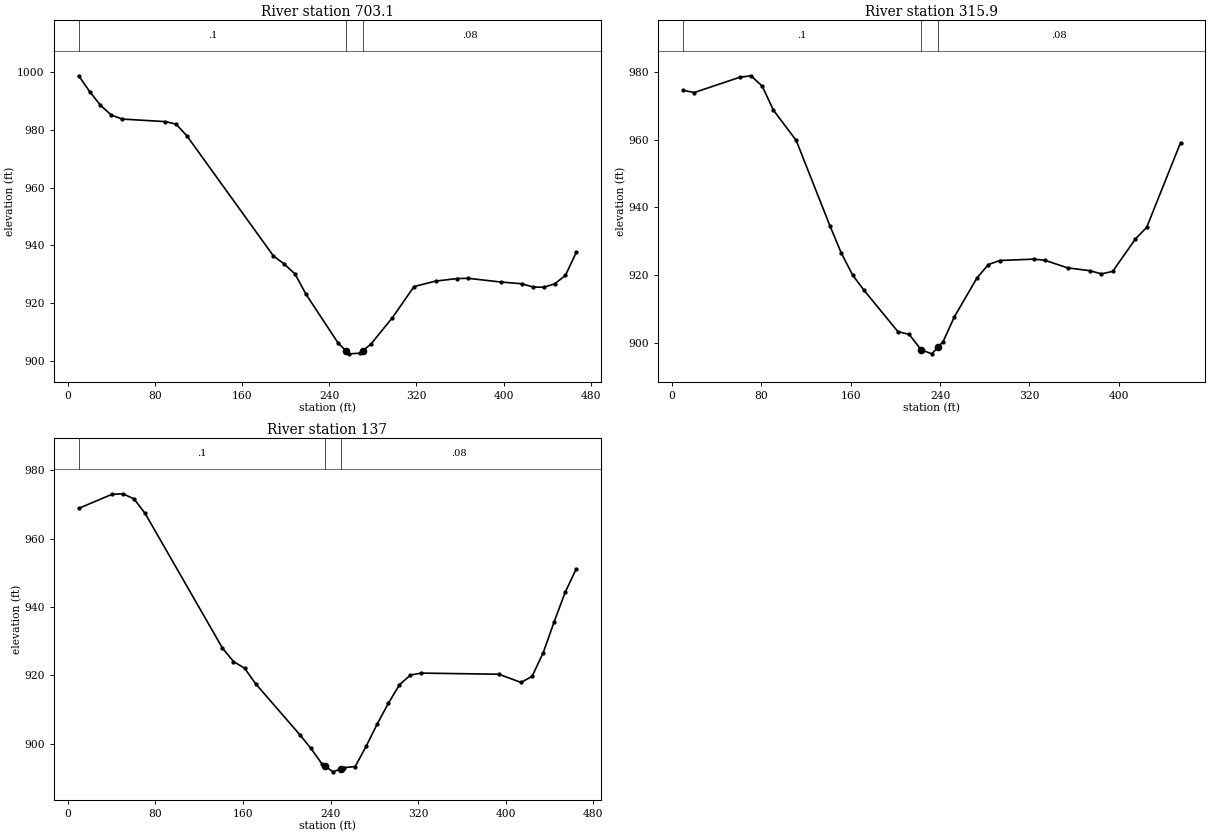
Type RM Length L Ch R = 1 ,703.1   ,397.1,387.2,377.3
XS GIS Cut Line= 2
     1641241.997      288137.499     1640944.253       288496.92
#Sta/Elev= 30
     9.9  998.54    19.9  993.11    29.8  988.39    39.7  985.03    49.7  983.61
    89.4  982.73    99.3  981.85   109.2  977.82   188.7  936.38   198.6   933.6
   208.5  930.17   218.5  923.21   248.3  906.23   255.7 903.533   258.2  902.62
   268.1  902.85   270.7 903.656   278.1  905.95   297.9  915.09   317.8  925.83
   337.6  927.71   357.5   928.6   367.4  928.68   397.2   927.4   417.1  926.78
     427  925.66   436.9  925.59   446.9  926.76   456.8  929.67   466.7  937.62
#Mann= 3 , 0 , 0
     9.9      .1       0   255.7    .045       0   270.7     .08       0
Bank Sta=255.7,270.7
XS Rating Curve= 0 ,0
Exp/Cntr=0.3,0.1

Type RM Length L Ch R = 1 ,315.9   ,178.9,178.9,178.9
XS GIS Cut Line= 2
     1640796.928      287948.407     1640681.704      288388.804
#Sta/Elev= 30
    10.1  974.55    20.2  973.93    60.7  978.42    70.8  978.87    80.9  975.83
      91  968.69   111.3  959.81   141.6  934.49   151.7  926.49   161.9  919.98
     172  915.53   202.3  903.32   212.4  902.49   223.2 897.936   232.7  896.75
   238.2  898.73   242.8  900.38   252.9  907.71   273.1  919.17   283.2   923.1
   293.4  924.31   323.7  924.72   333.8  924.38   354.1  922.15   374.3  921.29
   384.4  920.37   394.5   921.1   414.8  930.66   424.9   934.1   455.2  959.09
#Mann= 3 , 0 , 0
    10.1      .1       0   223.2    .045       0   238.2     .08       0
Bank Sta=223.2,238.2
XS Rating Curve= 0 ,0
Exp/Cntr=0.3,0.1

Type RM Length L Ch R = 1 ,137     ,138.9,137,135.1
XS GIS Cut Line= 2
     1640630.987      287878.305     1640513.208       288327.46
#Sta/Elev= 30
    10.1  968.86    40.4  972.95    50.5  973.12    60.6  971.61    70.7  967.38
   141.3     928   151.4  924.06   161.5  922.11   171.6  917.57     212  902.64
   222.1  898.64   232.2  894.11   234.8  893.52   242.3   891.8   249.8  892.72
   252.4  893.04   262.5  893.34   272.5  899.27   282.6  905.77   292.7  911.79
   302.8  917.21   312.9  920.11     323  920.68   393.7  920.34   413.9  917.95
     424  919.71   434.1  926.59   444.2  935.71   454.2  944.29   464.3  951.16
#Mann= 3 , 0 , 0
    10.1      .1       0   234.8    .045       0   249.8     .08       0
Bank Sta=234.8,249.8
XS Rating Curve= 0 ,0
Exp/Cntr=0.3,0.1

Chan Stop Cuts=-1
Use User Specified Reach Order=0